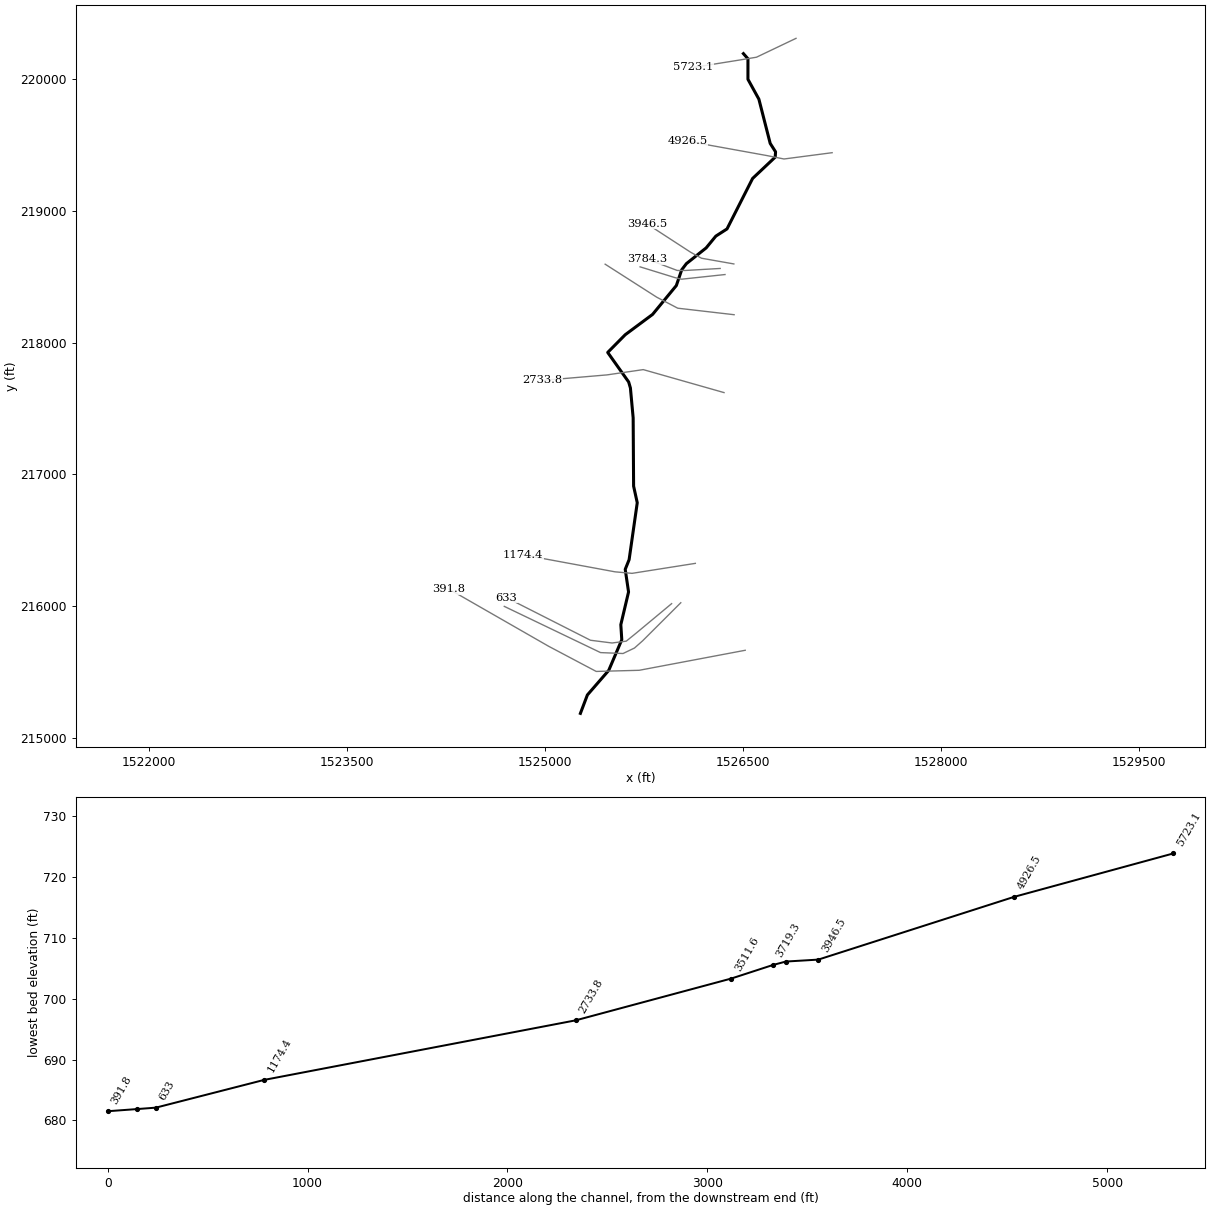
--- LMBRN.prj (project) ---

Proj Title=LMBRN
Current Plan=p01
Default Exp/Contr=0,0
English Units
Geom File=g01
Flow File=f01
Plan File=p01
BEGIN DESCRIPTION:
END DESCRIPTION:
DSS Export Rating Curves= 0
DSS Export Rating Curve Sorted= 0
DSS Export Volume Flow Curves= 0
DXF OffsetX= 0
DXF OffsetY= 0
DXF ScaleX= 0
DXF ScaleY= 0

--- LMBRN.p01 (plan) ---

Plan Title=Floodplain
Program Version=4.00
Geom File=g01
Flow File=f01
K Sum by GR=0
Std Step Tol=0.01
Critical Tol=0.01
Num of Std Step Trials=20
Max Error Tol=0.3
Flow Tol Ratio=0.001
Split Flow NTrial=30
Split Flow Tol=0.02
Split Flow Ratio=0.02
Log Output Level=0
Friction Slope Method=1
Unsteady Friction Slope Method=2
Unsteady Bridges Friction Slope Method=1
Global Log Level=0
CheckData=False
Run HTab=0
Run UNet=0
Run PostProcess=0
UNET Theta=0
UNET Theta Warmup=0
UNET ZTol=0
UNET ZSATol=0
UNET MxIter=0
UNET MaxInSteps=0
UNET DtIC=0
UNET DtMin=0
UNET MaxCRTS=0
UNET WFStab=0
UNET SFStab=0
UNET WFX=0
UNET SFX=0
UNET DSS MLevel=0
UNET DZMax Abort=0
UNET Convert EG Bridges=0
UNET Use Existing IB Tables=0
UNET Froude Limit=0
UNET Froude Power=0
Write IC File=0
Echo Input=False
Echo Output=False
Write Detailed=0

--- LMBRN.f01 (steady flow) ---

Flow Title=NFF Regression Equation
Program Version=4.10
Number of Profiles= 1
Profile Names=P100yr
River Rch & RM=LMBRN,Main            ,5723.1
890.3723
River Rch & RM=LMBRN,Main            ,3511.6
958.2217
River Rch & RM=LMBRN,Main            ,633
1044.283
River Rch & RM=LMBRN,Main            ,391.8
1044.855
Boundary for River Rch & Prof#=LMBRN,Main            , 1
Up Type= 0
Dn Type= 3
Dn Slope=0.00301
DSS Import GetInterval= 0
DSS Import GetPeak= 0
DSS Import FillOption= 0

--- LMBRN.g01 (geometry) ---

Geom Title=USGS 10m DEM
Program Version=4.10

River Reach=LMBRN           ,Main
Reach XY= 30
     1526504.756      220193.395     1526539.084      220154.296
     1526539.023      219998.527     1526621.923      219847.659
     1526707.638      219511.863     1526748.263      219447.974
     1526745.485      219407.696     1526574.327      219245.938
     1526380.468      218862.904     1526295.832      218808.217
     1526222.395      218718.634     1526072.749      218599.267
     1526037.242      218552.373     1525996.614      218432.956
     1525816.591      218213.924     1525609.756      218060.027
     1525476.775      217925.361      1525635.59      217701.012
     1525648.784      217655.526     1525669.603      217428.652
     1525672.978      216910.502     1525700.537      216784.592
     1525638.975      216352.314     1525609.462      216278.769
     1525634.707      216107.282     1525576.135      215858.963
      1525583.42      215744.675      1525484.63      215512.227
     1525322.941      215325.669     1525270.006      215185.676

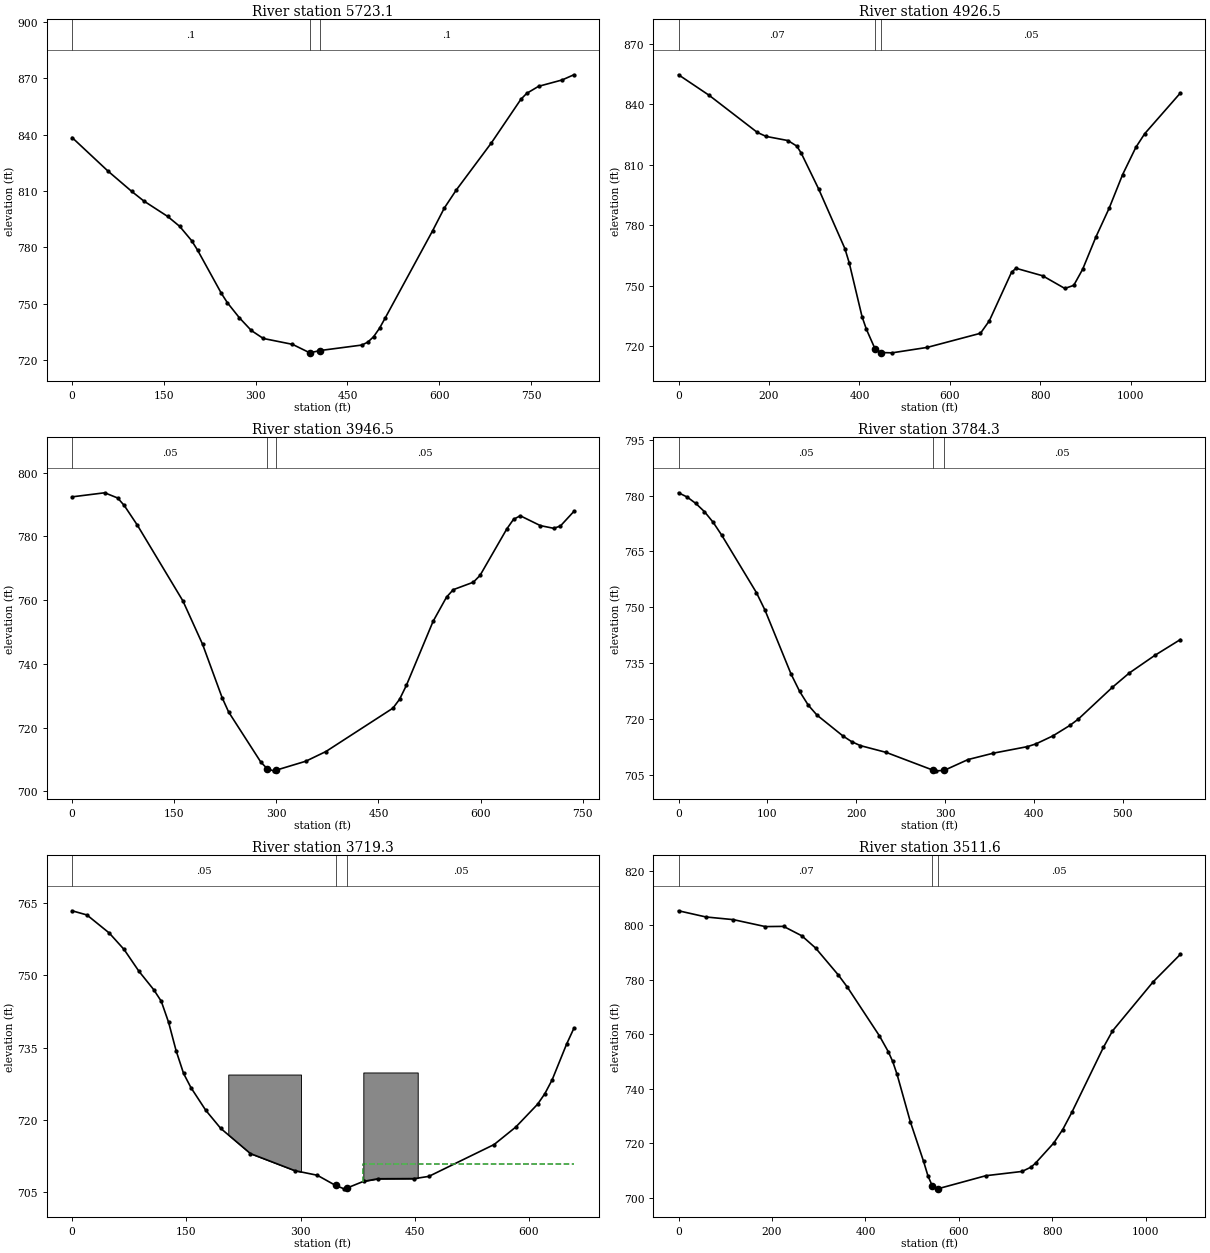
Type RM Length L Ch R = 1 ,5723.1  ,804.1,796.6,787.5
XS GIS Cut Line= 4
     1526903.304      220309.514     1526603.825      220166.284
     1526473.616      220144.583     1526122.054      220088.159
#Sta/Elev= 30
       0  838.56    58.6  820.71    97.6  809.83   117.2  804.77   156.2  796.54
   175.8  791.27   195.3  783.68     205  778.64   244.1  755.51   253.9  750.55
   273.4  742.58   292.9  735.81   312.4  731.57   360.2  728.43   388.5  723.91
   405.3  725.14   473.6  728.06   483.2   729.6   492.8  732.51   502.5  737.05
   512.1   742.7   589.1  788.86   608.3     801   627.6  810.49   685.3  835.73
   733.4  858.89     743  862.08   762.3  865.81   800.8   869.2     820  871.96
#Mann= 3 , 0 , 0
       0      .1       0   388.5    .045       0   405.3      .1       0
Bank Sta=388.5,405.3
XS Rating Curve= 0 ,0
Exp/Cntr=0.3,0.1

Type RM Length L Ch R = 1 ,4926.5  ,985.9,980,972.9
XS GIS Cut Line= 4
     1527176.741      219441.458     1526812.158      219393.715
      1526681.95      219419.757     1526082.991      219528.264
#Sta/Elev= 30
       0  854.53    67.7  844.35   174.2  825.97   193.5     824   241.9  821.94
   261.3  819.21   270.9  815.85   309.6  798.01   367.7  768.43   377.2  761.43
   405.6  734.73   415.1  728.53   434.1  718.87  447.73716.9211     472  716.77
   549.6  719.46   667.4  726.46     687  732.64   736.1  756.69   745.9  758.67
   804.8  754.95   853.9  748.67   873.6  750.21   893.2  758.13   922.6  774.18
   952.1  788.54   981.6  805.07    1011  818.63  1030.6  825.38  1109.2  845.48
#Mann= 3 , 0 , 0
       0     .07       0   434.1    .045       0  447.73     .05       0
Bank Sta=434.1,447.73
XS Rating Curve= 0 ,0
Exp/Cntr=0.3,0.1

Type RM Length L Ch R = 1 ,3946.5  ,150.1,162.3,173.1
XS GIS Cut Line= 4
     1526432.384      218597.093     1526187.158      218640.496
     1526104.693      218686.069     1525774.831      218900.913
#Sta/Elev= 30
       0  792.38    47.9  793.66      67  792.02    76.6  789.68    95.8  783.53
   162.8  759.73   191.6  746.17   220.3  729.44   229.9  724.91   277.3  709.16
   286.9  707.06   296.2  706.45  299.71706.6594   343.3  709.47   372.8  712.51
   471.2  726.11     481  728.91   490.9  733.23   530.2  753.35   549.9  760.93
   559.8  763.27   589.3  765.61   599.1  767.74   638.5  782.35   648.3  785.33
   658.2  786.45   687.7  783.36   707.4  782.51   717.2  783.25   736.9  787.81
#Mann= 3 , 0 , 0
       0     .05       0   286.9     .04       0  299.71     .05       0
Bank Sta=286.9,299.71
XS Rating Curve= 0 ,0
Exp/Cntr=0.3,0.1

Type RM Length L Ch R = 1 ,3784.3  ,71.4,65,59.1
XS GIS Cut Line= 4
     1526328.651      218562.805     1526066.064      218547.614
      1526003.13      218547.614     1525779.606      218632.249
#Sta/Elev= 30
       0  780.76     9.7  779.62    19.5  777.89    29.2  775.69      39  772.83
    48.7  769.35    87.7  753.96    97.4  749.23   126.6  732.16   136.4  727.43
   146.1  723.75   155.9  721.09   185.1  715.49   194.8  713.98   204.6  712.91
   233.8  711.08   286.3  706.33     290  706.13     299  706.24     326  709.16
   354.6  710.88   392.9  712.63   402.4  713.36   421.6  715.52   440.7  718.33
   450.2  720.03   488.5  728.55   507.6   732.4   536.3  737.12     565  741.36
#Mann= 3 , 0 , 0
       0     .05       0   286.3     .04       0     299     .05       0
Bank Sta=286.3,299
XS Rating Curve= 0 ,0
Exp/Cntr=0.3,0.1

Type RM Length L Ch R = 1 ,3719.3  ,212.6,207.6,202.1
XS GIS Cut Line= 4
     1526365.413      218516.595     1526035.552      218481.208
     1525986.073       218493.36     1525722.184      218574.958
#Sta/Elev= 30
       0  763.48    19.5  762.61    48.8  758.85    68.3  755.42    87.8  750.88
   107.3  747.03   117.1  744.64   126.8  740.22   136.6  734.34   146.4   729.6
   156.1  726.64   175.6  721.91   195.2  718.15   234.2   712.9   292.7  709.34
     322  708.39     346  706.27   357.2  705.56     361  705.73   382.7  707.12
   401.8  707.66   449.4  707.69   468.4  708.15   554.2  714.79   582.7  718.44
   611.3  723.19   620.8  725.38   630.4  728.27   649.4  735.72   658.9  738.99
#Mann= 3 , 0 , 0
       0     .05       0     346     .04       0     361     .05       0
#XS Ineff= 2 , 0
                          381.67          710.73
Permanent Ineff=
       F       F
#Block Obstruct= 2 ,-1
  205.07  300.58  729.37  382.44  453.87   729.8
Bank Sta=346,361
XS Rating Curve= 0 ,0
Exp/Cntr=0.3,0.1

Type RM Length L Ch R = 1 ,3511.6  ,763.8,777.8,789.1
XS GIS Cut Line= 4
     1526434.337      218211.676     1526007.253      218261.156
     1525848.399      218344.489     1525457.427      218595.154
#Sta/Elev= 30
       0  805.33    58.6  803.06   117.3  802.08   185.7  799.53   224.7  799.61
   263.8  796.15   293.1   791.7     342  781.77   361.5  777.27   429.9  759.45
   448.8  753.66   458.3  750.06   467.7  745.29     496  727.97   524.4  713.39
   533.8  708.06   543.2  704.35   552.7  703.34   555.8   703.4   657.7  708.16
   735.1  709.72   754.5  711.32   764.1   712.8   802.8  720.12   822.2   725.1
   841.5  731.35   909.3  755.26   928.6  761.24  1015.7  779.28  1073.8  789.34
#Mann= 3 , 0 , 0
       0     .07       0   543.2    .045       0   555.8     .05       0
Bank Sta=543.2,555.8
XS Rating Curve= 0 ,0
Exp/Cntr=0.3,0.1

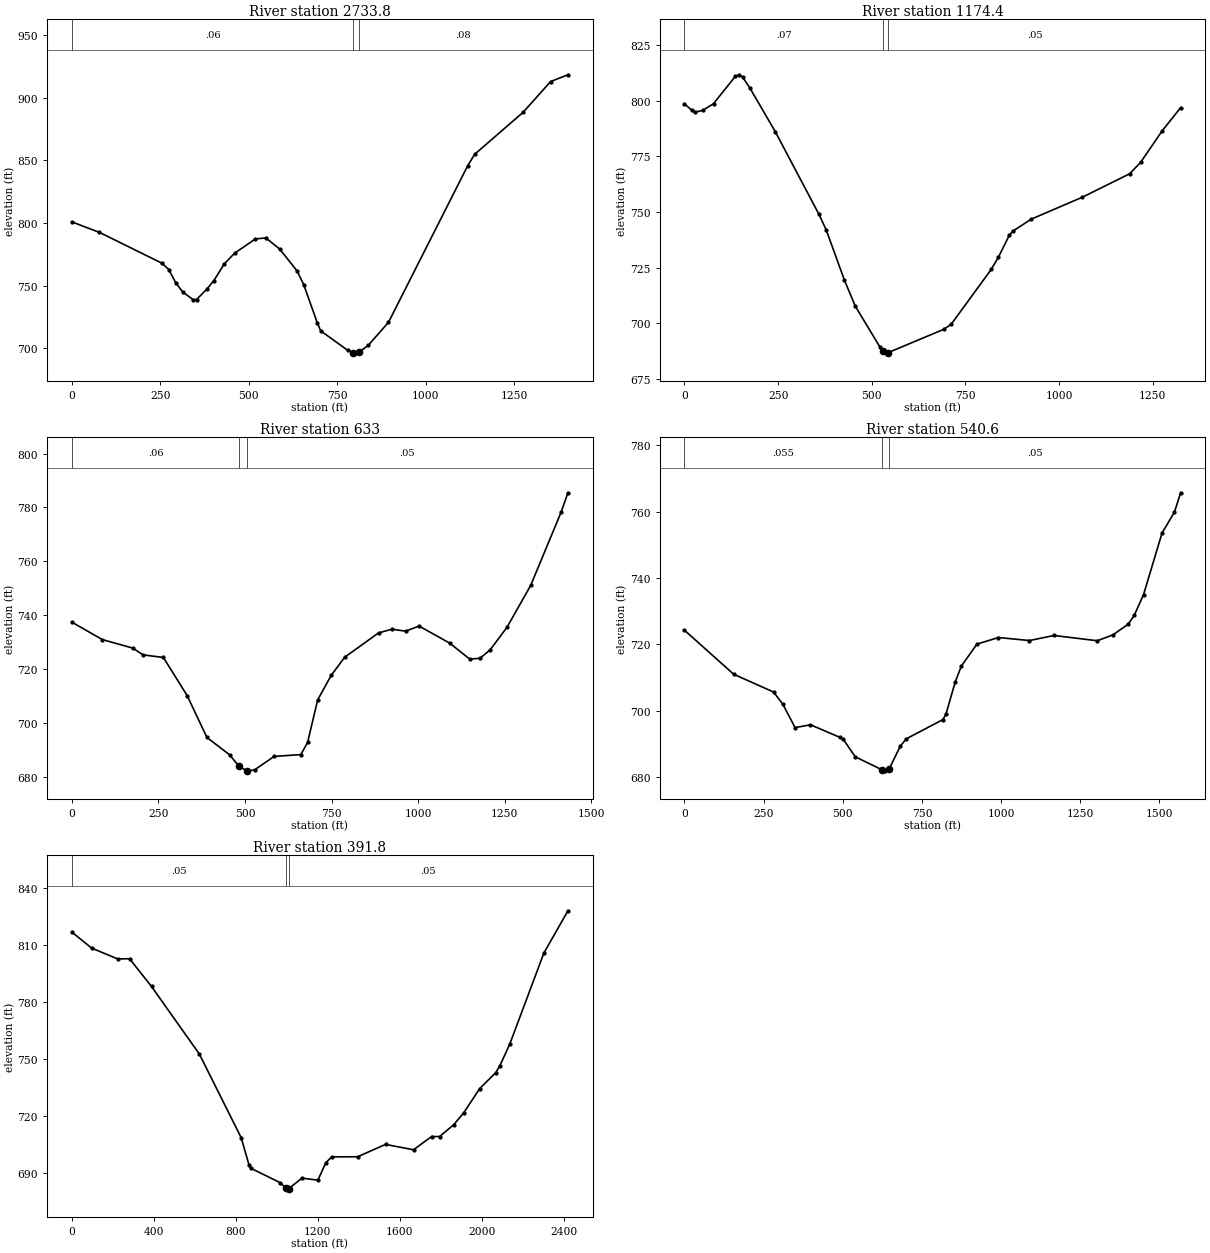
Type RM Length L Ch R = 1 ,2733.8  ,1561.7,1559.4,1555.6
XS GIS Cut Line= 4
     1526357.948      217620.531     1525745.969       217795.01
     1525471.316      217754.877     1524985.205       217713.21
#Sta/Elev= 30
       0  800.91    78.3  792.49   254.6  767.97   274.1  762.91   293.7  752.34
   313.3  745.03   342.7  738.89   352.4  738.91   381.8  747.36   401.4  754.05
   430.8  767.39   460.1  775.93   518.9  787.32   548.2  788.09   587.4  779.22
   636.4  761.83   655.5   750.7   693.8  720.27   703.4  713.97   779.9  698.43
   795.4  696.71   799.1  696.47   810.4   696.8   837.4  702.38   894.8  720.79
  1118.8  845.78  1138.4  854.81    1275  888.22    1353  912.79  1401.8  918.18
#Mann= 3 , 0 , 0
       0     .06       0   795.4    .045       0   810.4     .08       0
Bank Sta=795.4,810.4
XS Rating Curve= 0 ,0
Exp/Cntr=0.3,0.1

Type RM Length L Ch R = 1 ,1174.4  ,533.9,541.5,548.8
XS GIS Cut Line= 4
     1526140.587      216324.321      1525661.42      216248.569
     1525532.252      216260.102     1524834.163      216389.425
#Sta/Elev= 30
       0  798.59    19.4  795.71    29.1  794.92    48.5  795.61    77.6  798.67
   135.8  810.93   145.5  811.64   155.2  810.61   174.6  805.72   242.6  786.04
     359  748.96   378.4  741.95   426.9  719.43     456  707.68   522.2   689.2
   529.2  687.72   540.7  686.67   544.2  686.79   692.6  697.26   712.1  699.49
     819  724.13   838.5  729.71   867.7  739.62   877.4  741.44     926  746.75
  1062.2   756.6  1188.6  767.13  1217.8  772.24  1276.1  786.56  1324.8  796.84
#Mann= 3 , 0 , 0
       0     .07       0   529.2    .045       0   544.2     .05       0
Bank Sta=529.2,544.2
XS Rating Curve= 0 ,0
Exp/Cntr=0.3,0.1

Type RM Length L Ch R = 1 ,633     ,98.6,92.4,85.6
XS GIS Cut Line= 6
     1525960.899      216018.534     1525690.066       215792.84
     1525617.149      215733.812      1525509.51      215719.923
     1525346.316      215740.756     1524710.899      216063.673
#Sta/Elev= 30
       0  737.38    88.1   730.9   176.3  727.72   205.6  725.22   264.4  724.24
     333  710.09   390.1  694.52   455.4  688.08   482.7  683.81  504.99682.1255
   509.7  682.11   527.8  682.47   583.9  687.46   661.3  688.16   680.7  692.66
   709.7  708.46   748.7  717.56   787.8  724.34   885.4  733.37   924.4  734.76
   963.5  734.02  1002.6  735.92  1090.4  729.61    1149  723.63  1178.3  723.95
  1207.6  727.06  1256.4  735.49  1324.8  751.05  1412.6  778.28  1432.2  785.46
#Mann= 3 , 0 , 0
       0     .06       0   482.7    .045       0  504.99     .05       0
Bank Sta=482.7,504.99
XS Rating Curve= 0 ,0
Exp/Cntr=0.3,0.1

Type RM Length L Ch R = 1 ,540.6   ,146.4,148.8,151.8
XS GIS Cut Line= 6
     1526030.344      216025.479     1525742.149      215737.284
     1525679.649      215681.729     1525592.844      215640.062
     1525422.705      215647.006     1524693.538      215997.701
#Sta/Elev= 30
       0  724.25   155.3  710.99   281.4  705.62   310.5  701.99   349.3   694.9
   397.9  695.76   491.2  691.96   500.8   691.5   539.3  686.12   625.3  682.12
   634.8  681.88   646.3  682.43   682.1  689.38     701  691.55   816.2  697.32
     826  699.03   855.2   708.7   874.7  713.48   923.5  720.05   991.7  722.05
  1089.2  721.14  1167.2  722.66  1303.7  721.08  1352.4  722.81  1401.2  726.06
  1420.6  728.75  1449.9     735  1508.4  753.58  1547.4  759.82  1566.9  765.66
#Mann= 3 , 0 , 0
       0    .055       0   625.3    .045       0   646.3     .05       0
Bank Sta=625.3,646.3
XS Rating Curve= 0 ,0
Exp/Cntr=0.3,0.1

Type RM Length L Ch R = 1 ,391.8   ,400.9,391.8,381.9
XS GIS Cut Line= 5
     1526518.191      215664.599     1525715.239      215512.689
     1525389.719      215504.009     1525029.476      215694.981
     1524274.267      216129.009
#Sta/Elev= 30
       0  816.87    97.3   808.4   223.8  802.72   282.1  802.81   389.1  788.19
   622.6  752.58   826.8  708.48   865.1   694.1   874.7  692.32  1018.3  684.71
  1043.9  682.01  1056.6  681.52  1058.9  681.65  1123.7  687.18  1201.1  686.08
  1239.9  695.29    1269  698.38  1395.2  698.42  1531.2  704.94    1668  702.11
  1756.1   709.1  1795.2  709.08  1863.8  715.28  1912.7  721.55    1991  734.38
  2069.3  742.77  2088.8  746.27  2137.8  757.82  2304.2  805.81  2421.6  828.09
#Mann= 3 , 0 , 0
       0     .05       0  1043.9     .04       0  1058.9     .05       0
Bank Sta=1043.9,1058.9
XS Rating Curve= 0 ,0
Exp/Cntr=0.3,0.1

Chan Stop Cuts=-1
Use User Specified Reach Order=0
Composite Channel Slope=5